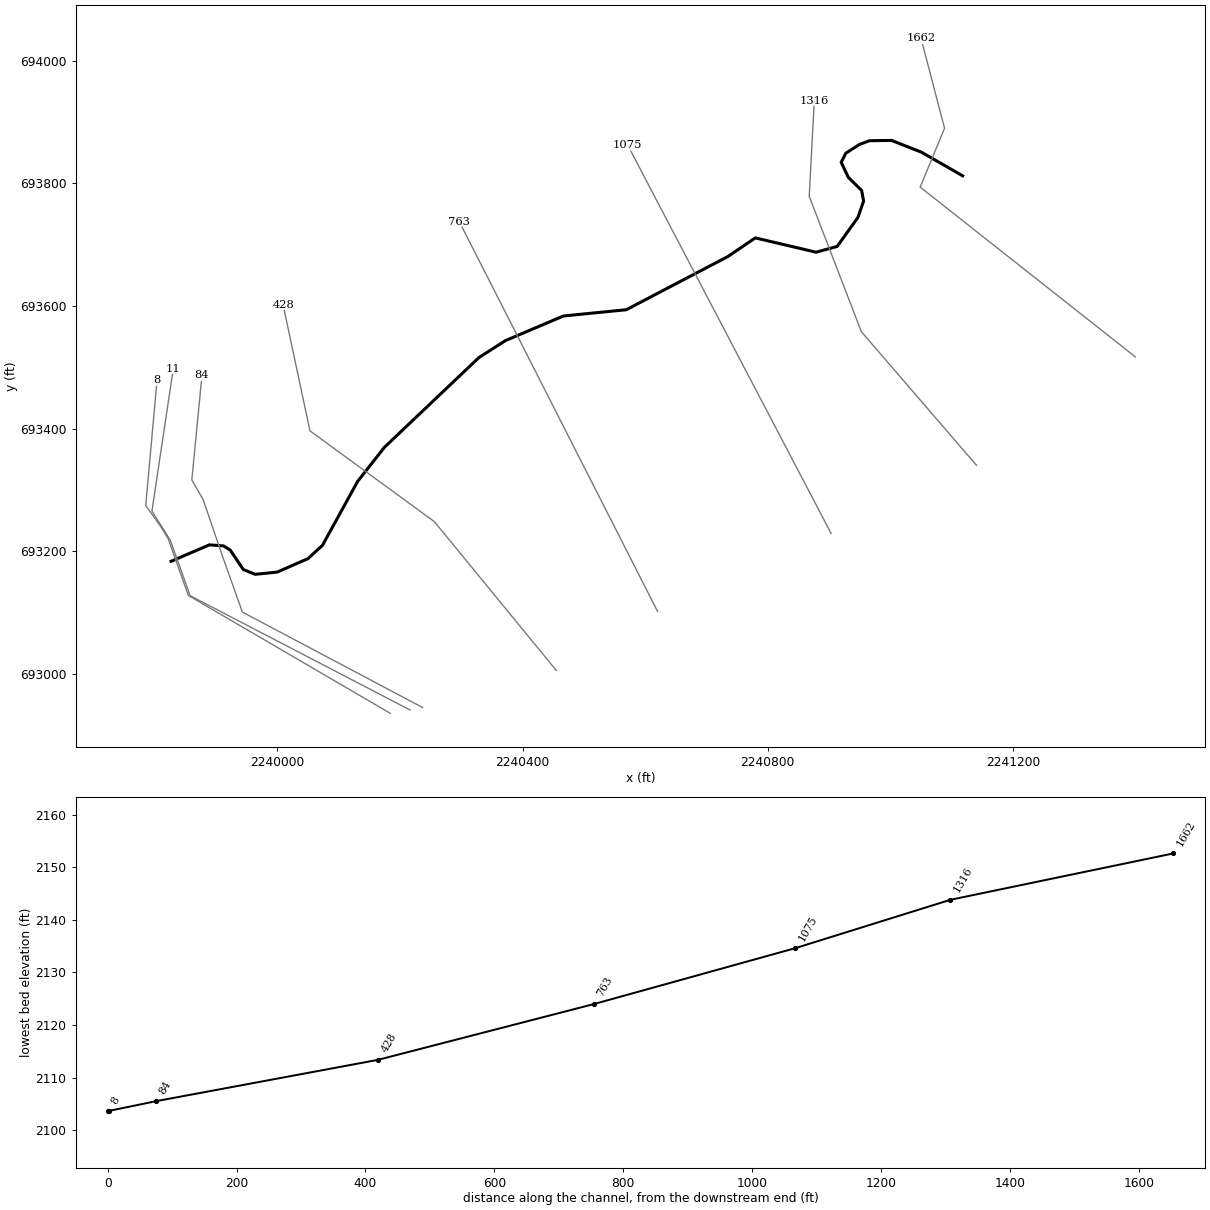
--- LAURLCKT1.prj (project) ---

Proj Title=LAURLCKT1
Current Plan=p01
Default Exp/Contr=0,0
English Units
Geom File=g01
Flow File=f01
Plan File=p01
BEGIN DESCRIPTION:
----------MODEL BY WSP USA 2022----------
AFH study
Randolph County, WV
HEC-RAS Version: RAS 6.2
Vertical Datum: NAVD88
Projection: NAD 1983 StatePlane West Virginia S FIPS 4702 (US Feet)
Terrain: 1-meter LIDAR (FEMA Region III 3DEP collected 2016-2018)
Land Use: 2019 NLCD
Hydrologic Method:
WV SIR2010-5033 regression equations
Additional Model Notes:
None
END DESCRIPTION:
DSS Export Rating Curves= 0
DSS Export Rating Curve Sorted= 0
DSS Export Volume Flow Curves= 0
DXF OffsetX= 0
DXF OffsetY= 0
DXF ScaleX= 0
DXF ScaleY= 0

--- LAURLCKT1.p01 (plan) ---

Plan Title=Floodplain
Program Version=6.20
Short Identifier=Floodplain
Geom File=g01
Flow File=f01
Subcritical Flow
K Sum by GR= 0
Std Step Tol= 0.01
Critical Tol= 0.01
Num of Std Step Trials= 20
Max Error Tol= 0.3
Flow Tol Ratio= 0.001
Split Flow NTrial= 30
Split Flow Tol= 0.02
Split Flow Ratio= 0.02
Log Output Level= 0
Friction Slope Method= 1
Unsteady Friction Slope Method= 2
Unsteady Bridges Friction Slope Method= 1
Parabolic Critical Depth
Global Vel Dist= 0 , 0 , 0
Global Log Level= 0
CheckData=True
Encroach Param=-1 ,0,0, 0
Computation Interval=1MIN
Output Interval=1HOUR
Instantaneous Interval=1HOUR
Mapping Interval=1HOUR
Computation Time Step Use Courant=        0
Computation Time Step Use Time Series=    0
Computation Time Step Count To Double=0
Computation Time Step Max Doubling=0
Computation Time Step Max Halving=0
Computation Time Step Residence Courant=0
Run HTab= 0
Run UNet= 0
Run Sediment= 0
Run PostProcess= 0
Run WQNet= 0
Run RASMapper=-1
UNET Theta= 1
UNET Theta Warmup= 1
UNET ZTol= 0.02
UNET ZSATol= 0.02
UNET MxIter= 20
UNET Max Iter WO Improvement= 0
UNET MaxInSteps= 0
UNET DtIC= 0
UNET DtMin= 0
UNET MaxCRTS= 20
UNET WFStab= 2
UNET SFStab= 1
UNET WFX= 1
UNET SFX= 1
UNET Gravity=32.174
UNET 1D Methodology=Finite Difference
UNET DSS MLevel= 4
UNET Pardiso=0
UNET DZMax Abort= 100
UNET Use Existing IB Tables=-1
UNET Froude Reduction=False
UNET Froude Limit= 0.8
UNET Froude Power= 4
UNET D1 Cores= 0
UNET WindReference=Eulerian
UNET WindDragFormulation=Hsu (1988)
UNET D2 Coriolis=0
UNET D2 Cores= 0
UNET D2 Theta= 1
UNET D2 Theta Warmup= 1
UNET D2 Z Tol= 0.01
UNET D2 Volume Tol= 0.01
UNET D2 Max Iterations= 20
UNET D2 Equation= 0
UNET D2 RampUpFraction=0.1
UNET D2 TimeSlices= 1
UNET D2 Turbulence Formulation=None
UNET D2 Eddy Viscosity=0.3
UNET D2 Transverse Eddy Viscosity=0.1
UNET D2 Smagorinsky Mixing=0.05
UNET D2 BCVolumeCheck=0
UNET D2 Cores=0
UNET D2 SolverType=PARDISO (Direct)
UNET D2 Minimum Iterations= 2147483647
UNET D2 Maximum Iterations= 2147483647
UNET D2 Restart Number= 10
UNET D2 Relaxation Coeff=1.3
UNET D2 SOR Precondition Iterations= 10
UNET D2 ILUT Maximum Fill= 8
UNET D2 ILUT Tolerance=1E-08
UNET D1D2 MaxIter= 0
UNET D1D2 ZTol=0.01
UNET D1D2 QTol=0.1
UNET D1D2 MinQTol=1
Write IC File= 0
Write IC File at Fixed DateTime=0
Write IC File at Sim End=0
Echo Input=False
Echo Parameters=False
Echo Output=False
Write Detailed= 0
HDF Write Warmup=0
HDF Write Time Slices=0
HDF Flush=0
HDF Compression= 1
HDF Chunk Size= 1
HDF Spatial Parts= 1
HDF Use Max Rows=0
HDF Fixed Rows= 1
Calibration Method= 0
Calibration Iterations= 20
Calibration Max Change=0.05
Calibration Tolerance=0.2
Calibration Maximum=1.5
Calibration Minimum=0.5
Calibration Optimization Method= 1
WQ AD Non Conservative
WQ ULTIMATE=-1
WQ Max Comp Step=1HOUR
WQ Output Interval=15MIN
WQ Output Selected Increments= 0
WQ Output face flow=0
WQ Output face velocity=0
WQ Output face area=0
WQ Output face dispersion=0
WQ Output cell volume=0
WQ Output cell surface area=0
WQ Output cell continuity=0
WQ Output cumulative cell continuity=0
WQ Output face conc=0
WQ Output face dconc_dx=0
WQ Output face courant=0
WQ Output face peclet=0
WQ Output face adv mass=0
WQ Output face disp mass=0
WQ Output cell mass=0
WQ Output cell source sink temp=0
WQ Output nsm pathways=0
WQ Output nsm derived pathways=0
WQ Create Restart=0
WQ Fixed Restart=0
WQ System Summary=0
WQ Write To DSS=0
Sorting and Armoring Iterations= 10
XS Update Threshold= 0.02
Bed Roughness Predictor= 0
Hydraulics Update Threshold= 0.02
Energy Slope Method= 1
Volume Change Method= 1
Sediment Retention Method= 0
Sediment TS Multiplier= 1
Warm Up Method= 0
XS Weighting Method= 0
Number of US Weighted Cross Sections= 1
Number of DS Weighted Cross Sections= 1
Upstream XS Weight=0
Main XS Weight=1
Downstream XS Weight=0
Number of DS XS's Weighted with US Boundary= 1
Upstream Boundary Weight= 1
Weight of XSs Associated with US Boundary= 0
Number of US XS's Weighted with DS Boundary= 1
Downstream Boundary Weight= 0.5
Weight of XSs Associated with DS Boundary= 0.5
Percentile Method= 0
Sediment Output Level= 3
Mass or Volume Output= 0
Output Increment Type= 1
Profile and TS Output Increment= 1
Transport Output Increment 1
XS Output Flag= 0
XS Output Increment= 10
Read HDF5 Sediment Hotstart= 0
Sediment Hotstart Type= 0
Write Gradation File= 0
Read Gradation Hotstart= 0
Write HDF5 File= 1
Write Binary Output= 1
Write DSS Sediment File= 0
DSS Sediment Output Type= 1
SV Curve= 0
Specific Gage Flag= 0
Subcell Erosion Methods= 0
Subcell Deposition Methods= 0
Advection Scheme= 1
Matrix Solver= 0
Implicit Weighting Factor= 1
Maximum Outer Loop Convergence Iterations= 5
Convergence Maximum Absolute= 0.001
Convergence RMSE= 0.0001
Grain Fractions Max Abs Error= 0.001
Max Subgrid Regions= 1
Max Subgrid Length Scale= 3.402823E+38
Initial Layer Thickness= 3.402823E+38
Min Layer Thickness= 3.402823E+38
Max Layer Thickness= 3.402823E+38
Number of Layers= 5

--- LAURLCKT1.f01 (steady flow) ---

Flow Title=Flow
Program Version=6.20
Number of Profiles= 1
Profile Names=P100yr
River Rch & RM=LAURLCKT1,Main,1662
     322
Boundary for River Rch & Prof#=LAURLCKT1,Main            , 1
Up Type= 0
Dn Type= 3
Dn Slope=0.02524
DSS Import GetInterval= 0
DSS Import GetPeak= 0
DSS Import FillOption= 0

--- LAURLCKT1.g01 (geometry) ---

Geom Title=Geometry
Program Version=6.20

River Reach=LAURLCKT1       ,Main
Reach XY= 30
2241117.96399999      693812.2062241050.77700001693850.748000011
2241001.81800002693870.0190000092240965.88100003693869.497999996
2240949.75099999693863.4969999942240927.33900003693849.186000004
2240919.75500001693834.3390000162240931.50600001693809.602000013
2240953.07600002693788.4420000172240956.39400002693771.180000007
2240947.13099998693744.4979999962240913.27700001693697.101999998
2240878.82200003693687.6560000182240779.73999999693711.000000015
     2240734.631693680.4360000042240569.25400002693593.819000021
2240466.66300002 693583.608000012240372.13100001693543.456000015
2240328.90200001693515.8520000132240174.73500003693369.498000011
2240130.98500004693313.7690000092240073.69400001693209.601999998
     2240050.126693187.8889999992239999.73500003693165.852000013
2239963.79799998693162.2060000152239944.52700001693170.019000009
2239923.17300002693201.790000007     2239912.235693208.560000017
     2239889.145693210.297000006     2239826.674      693183.453

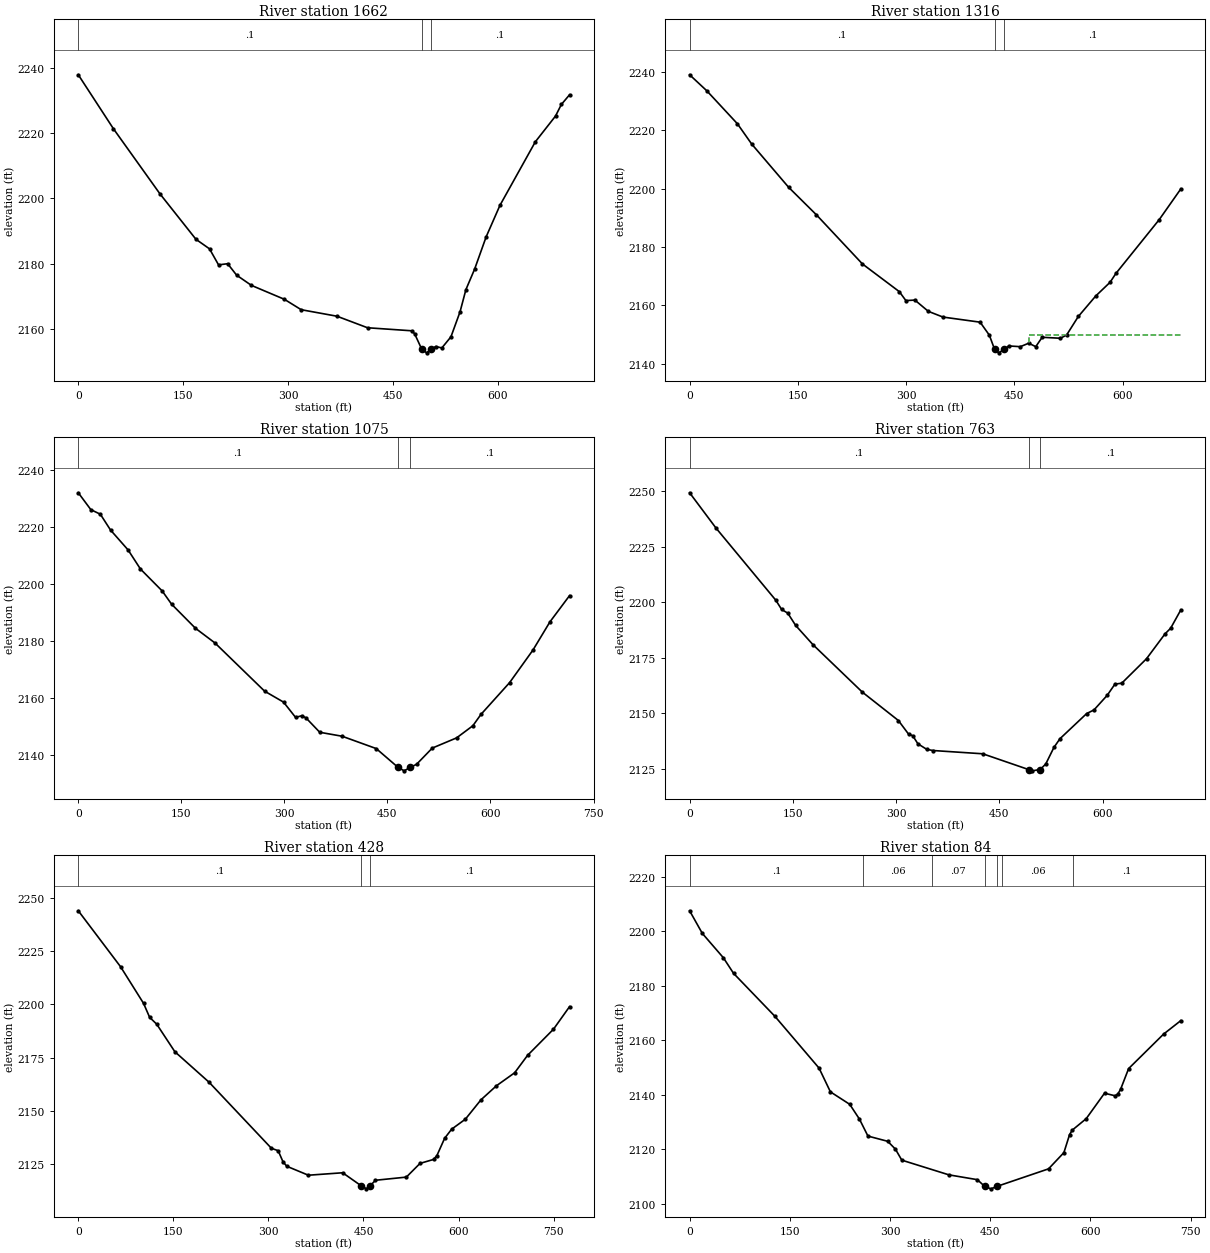
Type RM Length L Ch R = 1 ,1662    ,339.6,346,349.8
XS GIS Cut Line= 4
 2241399.6024347693516.8956033922241048.61917442693793.843332211
2241088.37899687693889.8153174452241049.99020278694036.515352017
#Sta/Elev= 30
       0 2237.97    50.2 2221.42   116.7 2201.45   168.3 2187.47   187.7 2184.54
   200.6 2179.62   213.6 2179.98   226.5 2176.45   247.6 2173.33   294.8 2169.05
   318.8 2165.86     370 2163.86   413.7 2160.32   476.9 2159.39     481  2158.5
     491 2153.84   498.2 2152.62   504.4 2153.76   511.3 2154.56     520 2154.13
     533 2157.54     546  2165.2   554.4 2172.03   566.9 2178.34   583.4 2188.25
   603.1  2197.9   653.7  2217.4   682.6 2225.31   690.9 2228.85   702.6 2231.82
#Mann= 3 ,-1,0
       0      .1       0     491    .045       0   504.4      .1       0
Bank Sta=491,504.4
XS Rating Curve= 0 ,0
Exp/Cntr(USF)=0,0
Exp/Cntr=0.3,0.1

Type RM Length L Ch R = 1 ,1316    ,237.5,240.8,240.9
XS GIS Cut Line= 4
2241140.47807457693340.0329448882240952.64718918693558.026454206
2240867.64343083693778.7620202452240875.86960099693935.059253341
#Sta/Elev= 30
       0 2238.93    23.7 2233.48    66.3 2222.15      86 2215.24   137.2 2200.44
   175.8    2191   239.5 2174.21   290.6 2164.74   299.7 2161.68   312.2 2161.85
   330.8    2158   351.1 2156.04   402.6 2154.29   415.4 2149.84   422.6 2145.02
   428.3  2143.8  436.34 2145.03   442.2 2146.16   458.3 2145.91     470  2147.1
   479.7 2145.91   488.6 2149.12     514 2148.79   522.5 2149.91   538.7 2156.24
   562.8 2163.24   582.8 2167.96   590.8 2170.97   650.9  2189.4   680.8  2199.9
#Mann= 3 ,0,0
       0      .1       0   422.6    .045       0  436.34      .1       0
#XS Ineff= 2 , 0
                          470.65         2149.91
Permanent Ineff=
       F       F
Bank Sta=422.6,436.34
XS Rating Curve= 0 ,0
Exp/Cntr(USF)=0,0
Exp/Cntr=0.3,0.1

Type RM Length L Ch R = 1 ,1075    ,311.9,312.1,311.6
XS GIS Cut Line= 2
 2240903.2901682693228.9796476892240571.50130496693862.394750235
#Sta/Elev= 30
       0 2231.88    18.3 2225.97    32.1 2224.38    46.9 2218.86    72.5 2211.88
    90.5  2205.2   122.1 2197.54   135.8 2192.91   170.5 2184.49   198.9 2179.35
   271.2 2162.48   298.8 2158.64   316.3  2153.3   325.3 2153.88   331.4 2153.14
   351.5 2148.09     384 2146.71   433.7 2142.39   465.3 2135.85   474.4  2134.6
   483.4 2135.85   492.4 2136.88   515.3 2142.56   550.7 2146.13   574.4 2150.38
   586.2 2154.35   627.9 2165.47   661.9 2176.87   686.6 2186.72   715.1 2195.89
#Mann= 3 ,-1,0
       0      .1       0   465.3    .045       0   483.4      .1       0
Bank Sta=465.3,483.4
XS Rating Curve= 0 ,0
Exp/Cntr(USF)=0,0
Exp/Cntr=0.3,0.1

Type RM Length L Ch R = 1 ,763     ,330.1,335.4,337.6
XS GIS Cut Line= 2
2240620.31675096693101.5288441422240296.75405788 693737.68600341
#Sta/Elev= 30
       0 2249.21    38.5 2233.25   125.3 2200.79   133.7 2196.65   142.6    2195
   154.1 2189.45   179.1 2180.83   250.9 2159.44   303.3 2146.65   318.1 2140.52
   324.1  2139.8   331.7 2136.15   344.4 2133.68   353.2 2133.14   425.9 2131.66
  492.39 2124.57   497.7 2123.98   509.3 2124.58   517.4 2127.05   529.3 2134.53
   538.1 2138.46   576.9 2149.79   587.5 2151.41   606.7 2157.99   617.9 2163.02
   627.9 2163.47   663.8 2174.47   690.7 2185.67   698.9 2188.22   713.7 2196.48
#Mann= 3 ,0,0
       0      .1       0  492.39    .045       0   509.3      .1       0
Bank Sta=492.39,509.3
XS Rating Curve= 0 ,0
Exp/Cntr(USF)=0,0
Exp/Cntr=0.3,0.1

Type RM Length L Ch R = 1 ,428     ,346.9,344,338.3
BEGIN DESCRIPTION:
Structure XS 4
END DESCRIPTION:
XS GIS Cut Line= 4
2240454.96389432693005.5020249292240256.16478205693248.174044736
 2240053.2525847693396.2451076692240009.37967716693601.899361742
#Sta/Elev= 30
       0 2243.99    66.8 2217.67     103 2200.49   112.6 2193.92   123.7 2190.74
   152.4 2177.77   206.4 2163.44   304.7 2132.43   315.4 2131.27     323 2126.11
     329 2123.97   363.1 2119.76   417.2 2120.91   446.1 2114.86   454.7 2113.36
   460.4 2114.77     469 2117.39   517.7 2118.87   539.3 2125.32   560.6 2127.17
   565.9 2128.97   578.1  2137.1   589.2 2141.39   610.8 2146.07   635.4 2155.17
   659.9 2161.79   688.6 2167.88     709 2176.08   749.9 2188.36   775.2 2198.94
#Mann= 3 ,-1,0
       0      .1       0   446.1    .045       0   460.4      .1       0
Bank Sta=446.1,460.4
XS Rating Curve= 0 ,0
Exp/Cntr(USF)=0,0
Exp/Cntr=0.3,0.1

Type RM Length L Ch R = 1 ,84      ,72.8,72.8,72.6
BEGIN DESCRIPTION:
Structure XS 3
END DESCRIPTION:
XS GIS Cut Line= 6
2240236.93111266692945.0062462722239943.00261532693100.637782402
2239911.03742887693190.4201160772239878.95536524693284.198455934
2239860.55806254693316.266941125 2239877.0920588693487.012485489
#Sta/Elev= 30
       0 2207.49      19  2199.2    50.6 2190.24    65.8 2184.54   127.6 2168.81
   193.8 2149.79   210.8 2141.08   239.7 2136.51   254.3 2131.07     267 2124.86
   296.6 2122.94   308.1 2120.08   317.7 2116.03   388.2 2110.64   430.8 2108.87
   441.8 2106.41   451.2 2105.51   460.4 2106.43   537.4 2112.84   560.4  2118.8
   568.9 2125.41   572.9 2127.04   593.8 2131.25   621.2 2140.58   637.2 2139.63
   641.1 2140.28   645.3 2142.03   657.3 2149.61   709.6 2162.25   735.5 2167.22
#Mann= 7 ,-1,0
       0      .1       0     260     .06       0  362.59     .07       0
   441.8    .045       0   460.4     .07       0  467.89     .06       0
  573.98      .1       0
Bank Sta=441.8,460.4
XS Rating Curve= 0 ,0
Exp/Cntr(USF)=0,0
Exp/Cntr=0.3,0.1

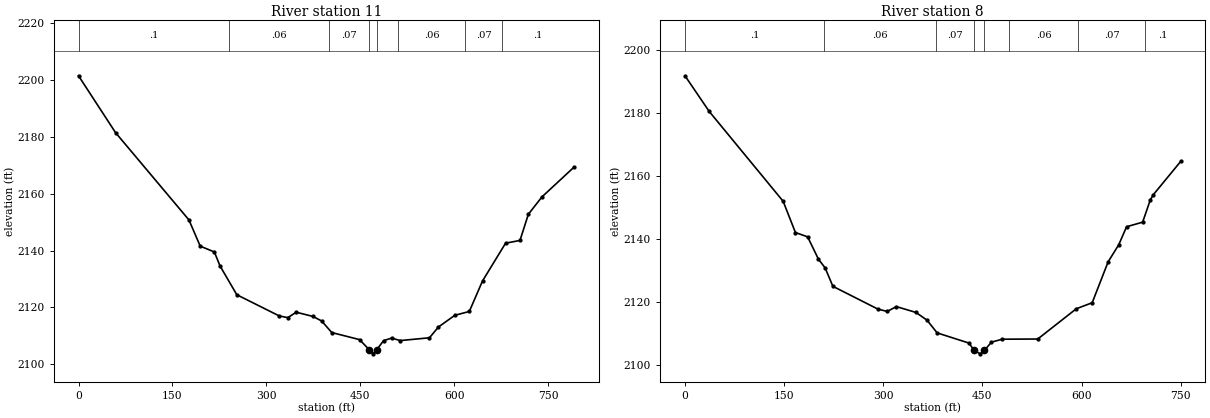
Type RM Length L Ch R = 1 ,11      ,3.7,2.6,2.7
BEGIN DESCRIPTION:
Structure XS 2
END DESCRIPTION:
XS GIS Cut Line= 5
2240216.58533448 692940.856979242239857.84637936693127.351603618
2239825.47023426693217.7816372082239795.48584401693265.534555004
2239830.28252234 693497.51241585
#Sta/Elev= 30
       0 2201.48    59.1 2181.49   176.3 2150.77   194.3 2141.55   216.9 2139.51
   225.9 2134.59   252.7 2124.46   320.5    2117   334.1 2116.41   347.6 2118.31
   374.3 2116.83   388.2 2115.22   404.3 2111.16   448.7 2108.67   464.1 2105.12
     470 2103.67  476.27 2105.16     487 2108.31   499.7  2109.2   513.8 2108.34
   560.3 2109.32   574.6 2113.11   600.9 2117.24   623.9 2118.57     645 2129.32
   681.8 2142.59   704.8 2143.56   718.2 2152.78   739.9 2158.88   791.3 2169.39
#Mann= 8 ,-1,0
       0      .1       0     240     .06       0     400     .07       0
   464.1    .045       0  476.27     .07       0  510.37     .06       0
  616.76     .07       0  676.76      .1       0
Bank Sta=464.1,476.27
XS Rating Curve= 0 ,0
Exp/Cntr(USF)=0,0
Exp/Cntr=0.3,0.1

Type RM Length L Ch R = 1 ,8       ,,,
XS GIS Cut Line= 6
2240184.48116066 692935.401674722239854.88922246693127.720137088
2239821.84929875 693220.572435162239810.17445915693239.465702926
2239785.35154345693274.6410969972239803.75592738693478.394664947
#Sta/Elev= 30
       0 2191.76    36.6 2180.47   148.6 2151.95   167.1 2142.06   185.6 2140.68
   201.9 2133.63   212.1 2130.83   223.8    2125   292.1 2117.76     306 2117.04
   319.9 2118.57   349.6 2116.71   366.2 2114.27   381.6 2110.23   429.8    2107
   437.4 2104.71   446.8 2103.59   453.1 2104.69   463.8 2107.31   480.2 2108.23
   533.8 2108.29   592.1 2117.88   616.2  2119.8   640.3 2132.77   656.4  2138.2
   668.2 2143.89   692.5 2145.34     704 2152.34   708.7 2154.06     750 2164.58
#Mann= 8 ,-1,0
       0      .1       0     210     .06       0     380     .07       0
   437.4    .045       0   453.1     .07       0  490.15     .06       0
  595.42     .07       0  695.42      .1       0
Bank Sta=437.4,453.1
XS Rating Curve= 0 ,0
Exp/Cntr(USF)=0,0
Exp/Cntr=0.3,0.1
LCMann Table=0

Chan Stop Cuts=-1
Use User Specified Reach Order=0
Composite Channel Slope=5